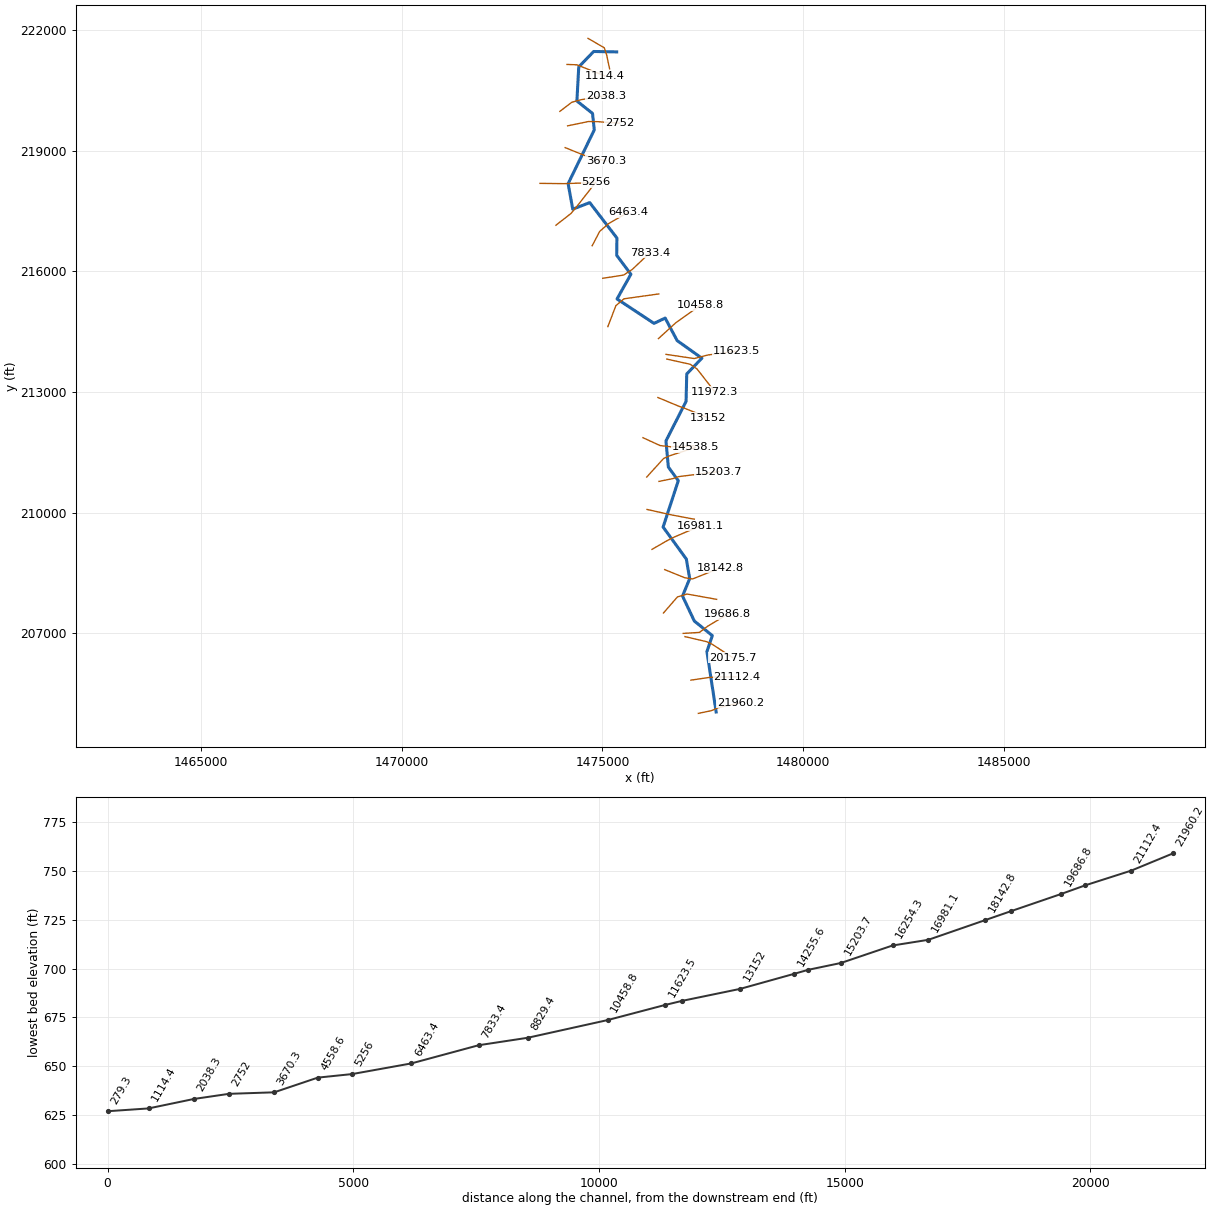
--- BRRN2.prj (project) ---

Proj Title=BRRN2
Current Plan=p01
Default Exp/Contr=0,0
English Units
Geom File=g01
Flow File=f01
Plan File=p01
BEGIN DESCRIPTION:
END DESCRIPTION:
DSS Export Rating Curves= 0
DSS Export Rating Curve Sorted= 0
DSS Export Volume Flow Curves= 0
DXF OffsetX= 0
DXF OffsetY= 0
DXF ScaleX= 0
DXF ScaleY= 0

--- BRRN2.p01 (plan) ---

Plan Title=Floodplain
Program Version=4.00
Geom File=g01
Flow File=f01
K Sum by GR=0
Std Step Tol=0.01
Critical Tol=0.01
Num of Std Step Trials=20
Max Error Tol=0.3
Flow Tol Ratio=0.001
Split Flow NTrial=30
Split Flow Tol=0.02
Split Flow Ratio=0.02
Log Output Level=0
Friction Slope Method=1
Unsteady Friction Slope Method=2
Unsteady Bridges Friction Slope Method=1
Global Log Level=0
CheckData=False
Run HTab=0
Run UNet=0
Run PostProcess=0
UNET Theta=0
UNET Theta Warmup=0
UNET ZTol=0
UNET ZSATol=0
UNET MxIter=0
UNET MaxInSteps=0
UNET DtIC=0
UNET DtMin=0
UNET MaxCRTS=0
UNET WFStab=0
UNET SFStab=0
UNET WFX=0
UNET SFX=0
UNET DSS MLevel=0
UNET DZMax Abort=0
UNET Convert EG Bridges=0
UNET Use Existing IB Tables=0
UNET Froude Limit=0
UNET Froude Power=0
Write IC File=0
Echo Input=False
Echo Output=False
Write Detailed=0

--- BRRN2.f01 (steady flow) ---

Flow Title=NFF Regression Equation
Program Version=4.10
Number of Profiles= 1
Profile Names=P100yr
River Rch & RM=BRRN2,Main            ,21960.2
895.6652
River Rch & RM=BRRN2,Main            ,20175.7
930.7472
River Rch & RM=BRRN2,Main            ,19686.8
1044.038
River Rch & RM=BRRN2,Main            ,18662.4
1053.994
River Rch & RM=BRRN2,Main            ,18142.8
1218.516
River Rch & RM=BRRN2,Main            ,16981.1
1260.522
River Rch & RM=BRRN2,Main            ,14538.5
1347.352
River Rch & RM=BRRN2,Main            ,14255.6
 1482.79
River Rch & RM=BRRN2,Main            ,11972.3
1528.153
River Rch & RM=BRRN2,Main            ,11623.5
1625.847
River Rch & RM=BRRN2,Main            ,7833.4
1755.553
River Rch & RM=BRRN2,Main            ,5256
1839.515
River Rch & RM=BRRN2,Main            ,279.3
1955.015
Boundary for River Rch & Prof#=BRRN2,Main            , 1
Up Type= 0
Dn Type= 3
Dn Slope=0.00113
DSS Import GetInterval= 0
DSS Import GetPeak= 0
DSS Import FillOption= 0

--- BRRN2.g01 (geometry) ---

Geom Title=USGS 10m DEM
Program Version=4.10

River Reach=BRRN2           ,Main
Reach XY= 30
     1477829.477      205039.617      1477599.99      206542.014
     1477734.132      206940.125     1477286.138      207302.808
     1476992.564      207923.856     1477170.915      208358.468
     1477087.656      208843.616     1476509.448      209640.233
     1476887.234      210793.534     1476640.015      211132.318
     1476580.204      211783.063     1477081.035      212767.061
     1477097.457      213448.764     1477474.473      213840.409
     1476859.556       214277.58      1476560.56      214838.909
     1476283.307      214706.854     1475362.646      215314.801
     1475707.673      215928.667     1475354.253      216398.647
     1475359.506      216830.243     1474682.886      217710.948
     1474260.389      217547.874     1474145.426       218181.58
     1474796.287       219519.17     1474752.443      219929.326
     1474363.794       220238.87     1474409.513      221085.917
     1474781.675      221470.038     1475354.291      221460.118

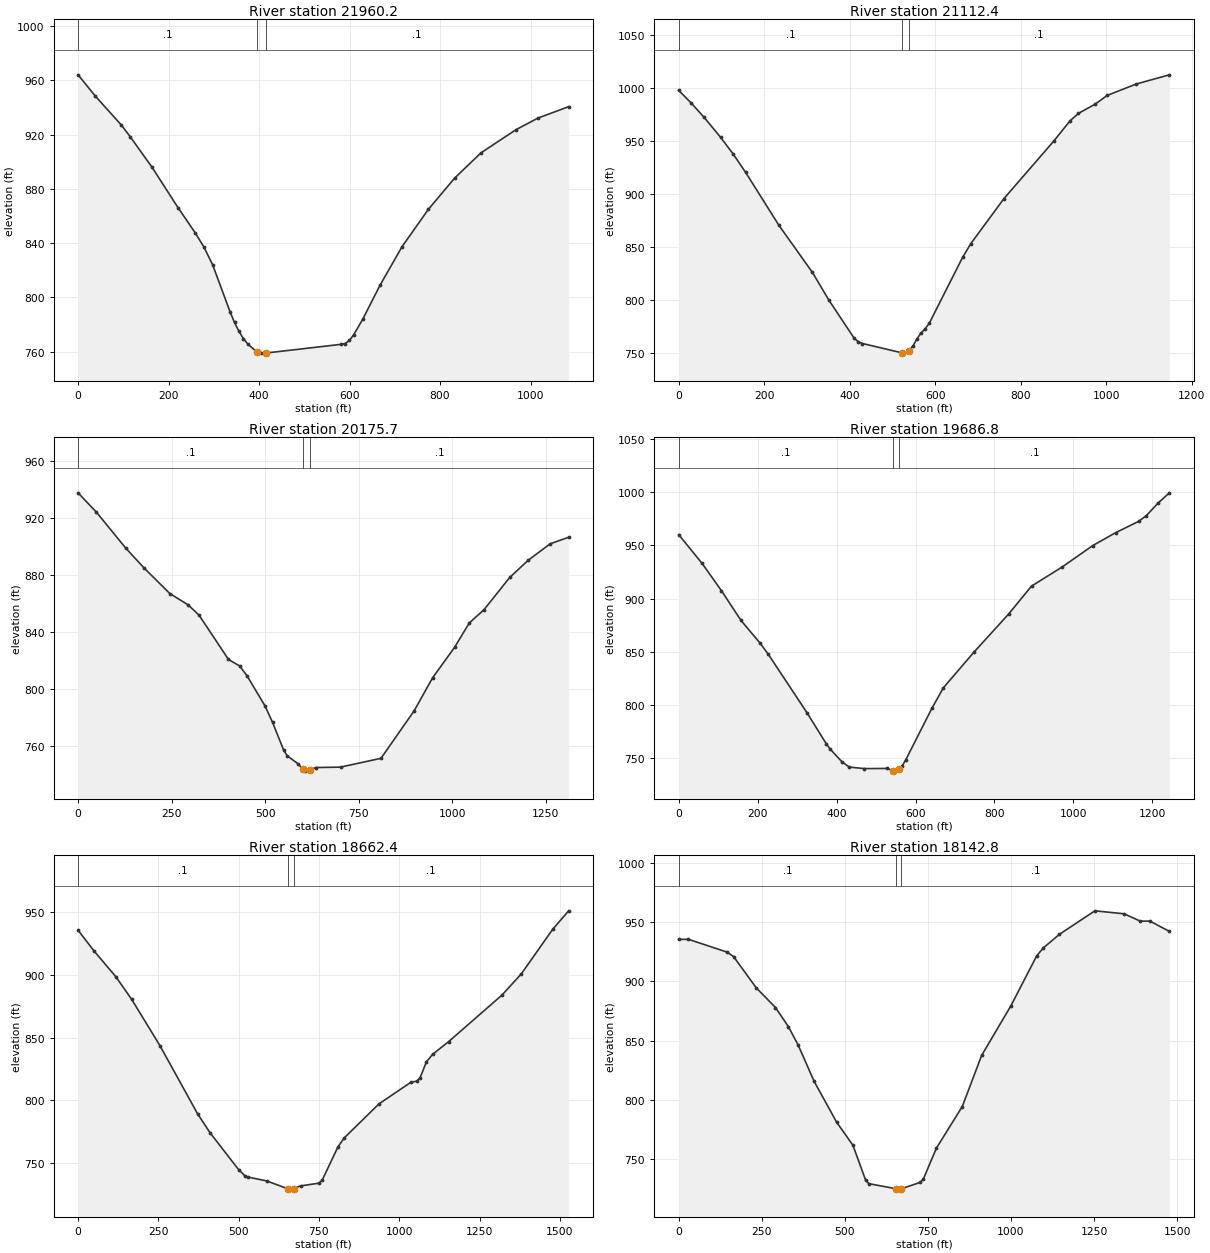
Type RM Length L Ch R = 1 ,21960.2 ,854.2,847.8,840.1
XS GIS Cut Line= 4
     1477386.087       205005.61     1477705.531      205071.582
     1477886.087      205147.971     1478434.698      205269.499
#Sta/Elev= 30
       0  964.06    38.4  948.28    95.9  926.93   115.1   918.5   163.1   896.1
   220.7  866.23     259   847.5   278.2  837.08   297.4  824.01     336  789.22
   345.8  781.48   355.6  774.93   365.4   769.6   375.2   765.5   394.8  759.89
   404.6  758.86   414.4   758.9   580.4  765.31     590  765.89   599.7  768.19
   609.4  772.56   628.8  783.66   667.6  809.07     716  837.34   774.1  864.84
   832.3  887.92   890.4  906.52   967.9  923.61  1016.3  932.16  1084.2  940.57
#Mann= 3 , 0 , 0
       0      .1       0   394.8    .045       0   414.4      .1       0
Bank Sta=394.8,414.4
XS Rating Curve= 0 ,0
Exp/Cntr=0.3,0.1

Type RM Length L Ch R = 1 ,21112.4 ,948.2,936.7,925.1
XS GIS Cut Line= 4
     1477202.059      205831.999     1477646.503      205897.971
     1477802.753      205908.388      1478344.42      205915.332
#Sta/Elev= 30
       0  998.07    29.3  986.06    58.6  972.94    97.7  953.88     127  938.16
   156.3  920.78   234.4  870.65   312.6  826.32   351.6  799.82   410.2  764.25
     420  760.71   429.8  759.14   522.6  750.31   527.6  750.07   537.6  751.74
   547.2   756.4     557  763.35   566.8  769.11   576.6  773.16   586.3  778.46
     664  840.45   683.3  853.49   760.7  895.92   876.8  950.02   915.5  969.42
   934.8  976.32   973.5  984.92  1002.5  993.37  1070.2 1004.08  1147.6 1012.76
#Mann= 3 , 0 , 0
       0      .1       0   522.6    .045       0   537.6      .1       0
Bank Sta=522.6,537.6
XS Rating Curve= 0 ,0
Exp/Cntr=0.3,0.1

Type RM Length L Ch R = 1 ,20175.7 ,459.6,488.9,521.5
XS GIS Cut Line= 4
     1477052.753      206915.332     1477587.476      206790.332
     1477726.364      206727.832     1478236.781      206394.499
#Sta/Elev= 30
       0  937.63      49  924.08   127.5  898.85   176.5  884.92   245.2  867.04
   294.2  859.08   323.6   851.8     402  820.82   431.5  816.32   451.1  809.56
   500.1  788.04   519.7  776.75   549.1  757.51   558.7  753.37   587.2  747.79
   600.9   743.8   606.2  742.54  619.79743.2791   634.8  745.06   701.4  745.34
   809.6  751.54   898.1  784.78   947.3  807.87  1006.2   829.3  1045.6  846.42
  1084.9  855.72  1153.7  878.32  1202.9  890.34  1261.9  901.92  1311.1  906.47
#Mann= 3 , 0 , 0
       0      .1       0   600.9    .045       0  619.79      .1       0
Bank Sta=600.9,619.79
XS Rating Curve= 0 ,0
Exp/Cntr=0.3,0.1

Type RM Length L Ch R = 1 ,19686.8 ,1032.1,1024.4,1016.5
XS GIS Cut Line= 4
     1477011.087      206995.194     1477413.864      207019.499
     1477611.781      207168.805     1478118.726       207474.36
#Sta/Elev= 30
       0  959.93      59  933.04   108.3  907.34   157.5   879.6   206.7  857.92
   226.4  848.04   324.8  793.01     374   763.7   383.8  758.78     413  747.14
   432.1  741.92   470.3  740.51   527.5  740.64   544.2  738.49   546.5  738.13
   559.2  740.13   565.6  742.63   575.2  748.67   641.9  797.32   670.8  816.38
   748.5  849.87   835.8  885.37     894  911.68   971.6  929.58  1049.3  949.72
  1107.5  961.84  1165.7  972.44  1185.1  977.83  1214.2  989.34  1243.3  999.18
#Mann= 3 , 0 , 0
       0      .1       0   544.2    .045       0   559.2      .1       0
Bank Sta=544.2,559.2
XS Rating Curve= 0 ,0
Exp/Cntr=0.3,0.1

Type RM Length L Ch R = 1 ,18662.4 ,527.4,519.6,509.1
XS GIS Cut Line= 4
     1476518.031      207502.138     1476865.253      207901.444
     1477104.837       207974.36     1477840.948      207842.416
#Sta/Elev= 30
       0   935.8      49  919.48   117.6  898.69   166.6  880.78   254.8  843.77
   372.4  789.24   411.6  774.03   499.8   744.9   519.4  739.97   529.2  738.91
     587  735.87   654.4  729.49     664  729.31   671.3  729.79   692.9  731.89
   750.7  734.08   760.3  736.58   809.1  762.98   828.8  770.19     937  797.32
  1035.4  814.38  1055.1  815.54    1065  818.18  1084.6  830.82  1104.3  836.91
  1153.5  846.88  1320.8  884.29  1379.8  900.92  1478.2  936.65  1527.4  951.25
#Mann= 3 , 0 , 0
       0      .1       0   654.4    .045       0   671.3      .1       0
Bank Sta=654.4,671.3
XS Rating Curve= 0 ,0
Exp/Cntr=0.3,0.1

Type RM Length L Ch R = 1 ,18142.8 ,1147.6,1161.7,1174.2
XS GIS Cut Line= 4
     1476549.281      208581.999     1477052.753      208377.138
     1477243.726       208349.36     1477931.226      208623.666
#Sta/Elev= 30
       0  935.29    29.1  935.34   145.6  924.56     165  920.81     233  894.56
   291.2  877.84     330  861.76   359.1   846.4   407.7  815.54   475.6  781.03
   524.1  761.87   562.8  732.12   572.5  729.36   655.4  725.06   659.3  724.78
   670.4  725.13   726.9  730.46   736.5  733.37   775.5  759.29   853.4  794.38
   911.8  837.53   999.5  879.13  1077.4  921.38  1096.9  927.95  1145.6   939.5
  1252.7  959.36  1340.4  956.87  1389.1  950.68  1418.3  950.67  1476.7  942.08
#Mann= 3 , 0 , 0
       0      .1       0   655.4    .045       0   670.4      .1       0
Bank Sta=655.4,670.4
XS Rating Curve= 0 ,0
Exp/Cntr=0.3,0.1

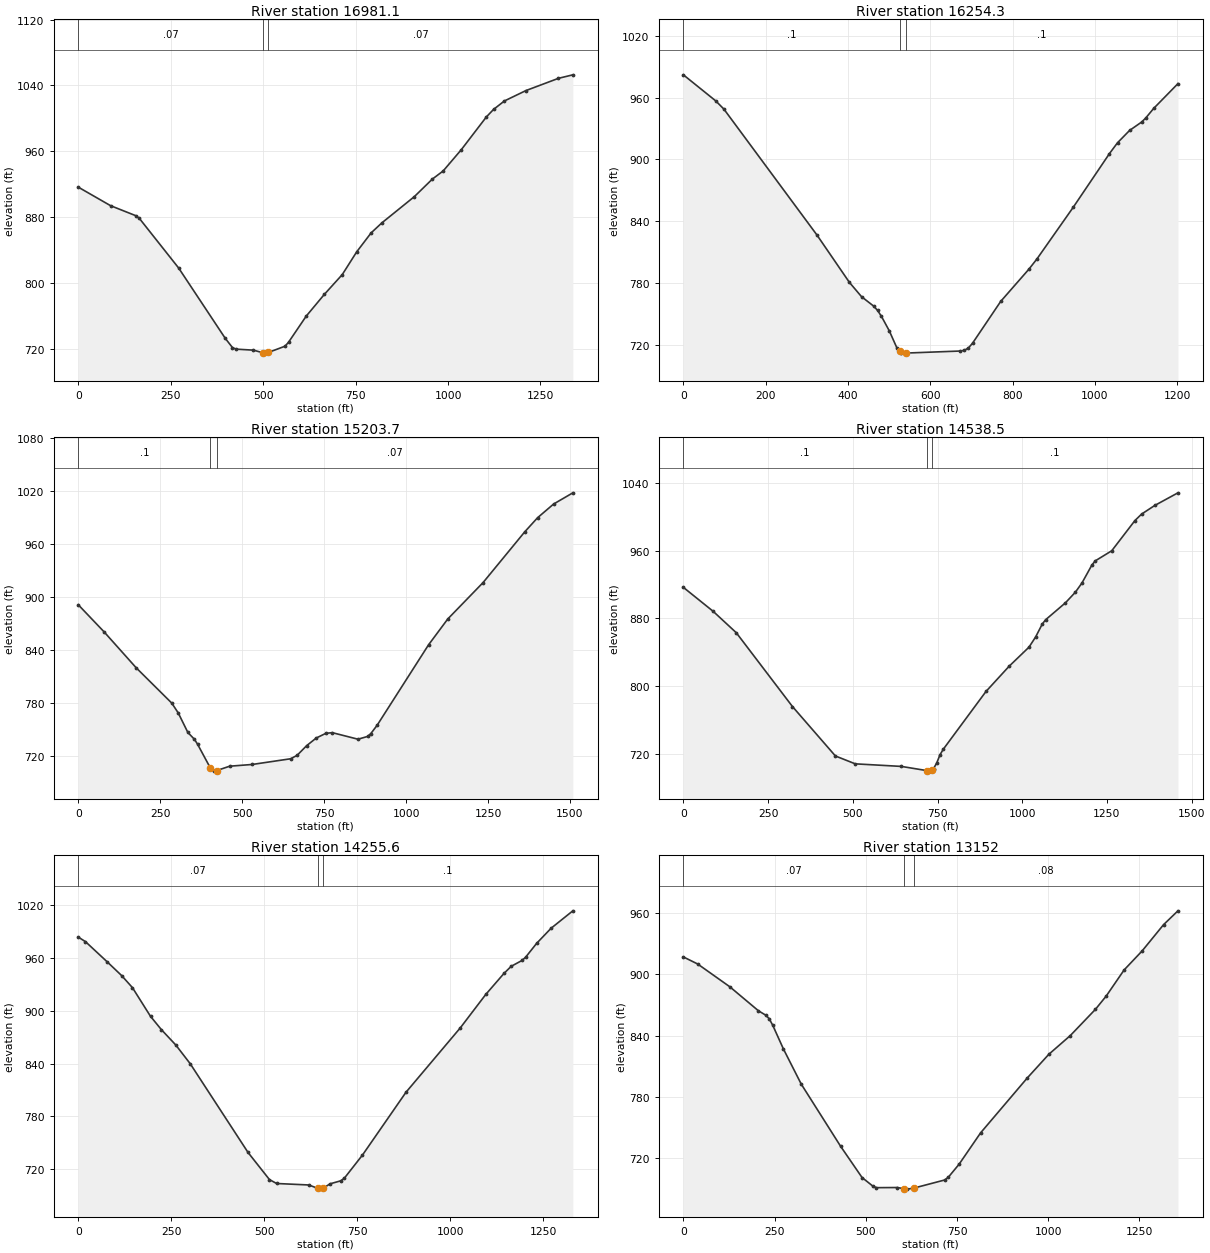
Type RM Length L Ch R = 1 ,16981.1 ,741.4,726.8,709.8
XS GIS Cut Line= 4
     1476233.309      209085.471      1476594.42      209293.805
     1476754.142      209377.138     1477434.698      209668.805
#Sta/Elev= 30
       0  916.39    87.3  893.87   155.1  881.78   164.8  878.64   271.5  818.08
   397.5  732.64   416.9  721.48   426.4  719.53   473.8  718.28     499  715.16
   502.2  714.67     514  715.48   559.1  723.08   568.6  727.87   616.5  759.67
   665.2  785.93     714  810.16   752.9  837.72   791.9  860.76   821.1     873
   908.8  904.83   957.5  926.16   986.8  936.06  1035.5  961.72  1103.7 1001.75
  1123.1 1010.87  1152.4 1021.12  1210.8 1033.78  1298.5 1048.62  1337.5 1052.88
#Mann= 3 , 0 , 0
       0     .07       0     499    .045       0     514     .07       0
Bank Sta=499,514
XS Rating Curve= 0 ,0
Exp/Cntr=0.3,0.1

Type RM Length L Ch R = 1 ,16254.3 ,1035,1050.5,1058.5
XS GIS Cut Line= 4
     1476108.309      210078.527     1476559.698      209977.832
     1476698.587      209946.582     1477285.392      209835.471
#Sta/Elev= 30
       0  982.02    78.7   956.7    98.4  948.79   324.7  826.45   403.4  780.55
     433   766.6   462.5  757.43     472  753.24   481.5  747.43   500.4  733.51
   519.4  716.45   525.8  713.69   528.9  712.35   538.4  711.77   540.8  711.82
   673.4  713.82   683.2  714.52     693  716.83   702.8  721.38   771.3     762
   839.8  793.27   859.4  803.24   947.5  853.36  1035.6  905.53  1055.2  916.04
  1084.6  928.04    1114  936.21  1123.8   940.1  1143.3  949.48  1202.1  973.47
#Mann= 3 , 0 , 0
       0      .1       0   525.8    .045       0   540.8      .1       0
Bank Sta=525.8,540.8
XS Rating Curve= 0 ,0
Exp/Cntr=0.3,0.1

Type RM Length L Ch R = 1 ,15203.7 ,663,665.2,666.5
XS GIS Cut Line= 4
      1476406.92      210776.444     1476754.142      210845.888
     1476893.031      210894.499     1477893.031      211019.499
#Sta/Elev= 30
       0  891.43    78.7  860.75     177  819.86   285.2  779.98   304.9  768.88
   334.4  746.64   354.1  739.04   363.9   733.4   403.2  706.24     413  702.83
   422.8  703.53     462  708.42   530.6  710.38     648  716.85   667.6  720.72
   696.9  731.73   726.3  740.41   755.6   745.7   775.2  746.43   853.5  739.01
   882.8  742.16   892.6  745.38   912.2  755.03  1068.7     846  1127.4  875.34
  1235.1   916.6  1362.3  974.15  1401.4  990.12  1450.3 1005.64    1509 1018.34
#Mann= 3 , 0 , 0
       0      .1       0   403.2    .045       0   422.8     .07       0
Bank Sta=403.2,422.8
XS Rating Curve= 0 ,0
Exp/Cntr=0.3,0.1

Type RM Length L Ch R = 1 ,14538.5 ,295.2,282.9,270.4
XS GIS Cut Line= 4
     1476101.364      210884.082     1476521.503      211345.888
     1476677.753      211415.332     1477309.698      211620.194
#Sta/Elev= 30
       0  916.45    87.8  888.19   156.1  862.89   321.9  775.66   448.7  717.24
   507.3  707.94   643.3  704.91     719  699.93   728.8  699.34     734  700.96
   738.3   702.3   747.8  709.03   757.3  718.61   766.8  725.07     893  793.42
   961.4  823.28    1020  845.81  1039.6  857.88  1059.1  873.05  1068.9  878.14
  1127.5  898.18  1156.8   910.7  1176.3  921.62  1205.6  942.83  1215.4  947.73
  1264.2  959.69  1332.6  995.37  1352.2    1003  1391.2 1013.24  1459.6 1028.15
#Mann= 3 , 0 , 0
       0      .1       0     719    .045       0     734      .1       0
Bank Sta=719,734
XS Rating Curve= 0 ,0
Exp/Cntr=0.3,0.1

Type RM Length L Ch R = 1 ,14255.6 ,1108,1103.7,1096.7
XS GIS Cut Line= 4
     1476007.614      211863.249     1476431.226      211668.805
      1476688.17      211637.555     1477292.337       211661.86
#Sta/Elev= 30
       0   983.9    19.4  978.69    77.7  955.78   116.5  940.16   145.7  926.37
   194.2   893.8   223.3  878.73   262.2  861.17     301  839.89   456.4     739
     514  708.15   533.2  703.71   619.5  702.04     644  698.23   648.2  697.31
     659  698.54     677  703.36   705.8  706.78   715.4  709.79     764  736.04
     881  807.46  1027.3  880.82  1095.5  918.69  1144.3  942.52  1163.8  950.65
  1193.1  957.36  1202.8   961.1  1232.1  976.69  1271.1  993.94  1329.6 1013.75
#Mann= 3 , 0 , 0
       0     .07       0     644    .045       0     659      .1       0
Bank Sta=644,659
XS Rating Curve= 0 ,0
Exp/Cntr=0.3,0.1

Type RM Length L Ch R = 1 ,13152   ,1184.1,1179.6,1173.6
XS GIS Cut Line= 4
     1476379.142      212863.249     1476903.448      212644.499
     1477024.976      212602.832     1477636.087      212356.305
#Sta/Elev= 30
       0  917.03    39.2  910.12   127.3   887.8   205.7   864.3   225.3  860.08
   235.1  856.64   244.9  850.11   274.3  826.81   323.2  792.36     431  731.52
   489.8   700.9   519.1   692.6   528.9  691.01   586.5  691.15   604.8  689.99
     614  689.58   632.4  690.66   716.2  698.54   726.1  701.21   755.6  713.94
   814.6  744.69   942.5  798.45  1001.5  821.62  1060.5  840.01  1129.3  865.69
  1158.8  878.67    1208  904.31  1257.2  922.86  1316.2  948.69  1355.5   962.2
#Mann= 3 , 0 , 0
       0     .07       0   604.8    .045       0   632.4     .08       0
Bank Sta=604.8,632.4
XS Rating Curve= 0 ,0
Exp/Cntr=0.3,0.1

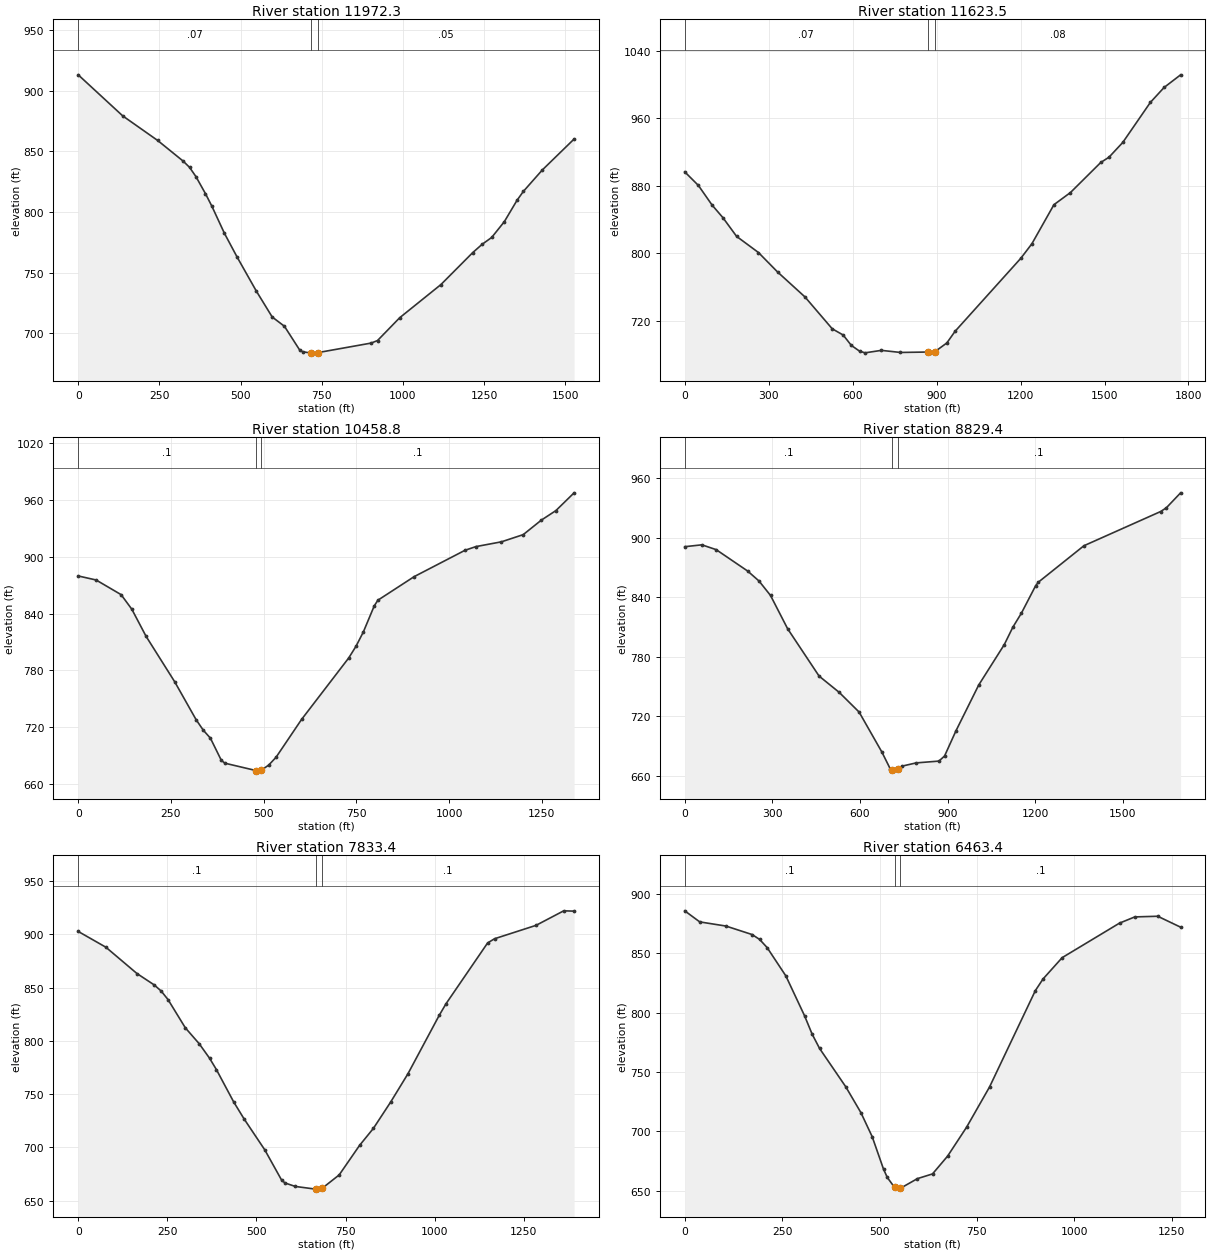
Type RM Length L Ch R = 1 ,11972.3 ,330,348.8,367.5
XS GIS Cut Line= 4
     1476601.364       213818.11     1477184.698      213689.638
     1477354.837      213571.582     1477799.281      213002.138
#Sta/Elev= 30
       0  913.23   137.1  879.32   244.8  859.01   323.1     842   342.7  836.88
   362.3  829.27   391.7  815.19   411.3   804.9   450.4  782.28   489.6   762.6
   548.4   734.7   597.3  713.29     635  705.62     682  685.98   691.4  684.58
   716.1  683.55   719.7  683.46   738.5  683.91     902  691.76   921.5  693.83
   989.9   712.7  1116.8  740.07  1214.4  766.38  1243.7  773.31    1273  778.95
    1312  791.99    1351   809.6  1370.6  816.98  1429.1  834.72  1526.8  860.22
#Mann= 3 , 0 , 0
       0     .07       0   716.1    .045       0   738.5     .05       0
Bank Sta=716.1,738.5
XS Rating Curve= 0 ,0
Exp/Cntr=0.3,0.1

Type RM Length L Ch R = 1 ,11623.5 ,1152.3,1164.7,1174.5
XS GIS Cut Line= 4
     1476580.531      213936.166     1477285.392      213831.999
     1477615.253      213918.805     1478327.059      214016.027
#Sta/Elev= 30
       0  896.57    48.8   880.4    97.6  857.16   136.6  842.07   185.4  819.92
   263.5  800.75   331.9  777.63   429.5   748.1   527.1  710.21   566.1  702.86
   595.4  690.48   624.7  683.71   644.2   681.7   702.8  684.63     771  682.15
   868.4  682.65   878.2  681.35   893.6  683.01   936.7  693.46   965.9  707.21
  1201.2  794.03  1240.6  811.22  1319.3  857.56  1378.4     872  1486.6  907.66
  1516.2  913.96  1565.4   931.5  1663.8  978.94    1713  996.73    1772 1011.72
#Mann= 3 , 0 , 0
       0     .07       0   868.4    .045       0   893.6     .08       0
Bank Sta=868.4,893.6
XS Rating Curve= 0 ,0
Exp/Cntr=0.3,0.1

Type RM Length L Ch R = 1 ,10458.8 ,1629.6,1629.4,1628.1
XS GIS Cut Line= 4
     1476393.031      214328.527      1476656.92       214568.11
     1476823.587      214720.888      1477438.17      215158.388
#Sta/Elev= 30
       0  879.74    48.2  875.49   115.6  860.02   144.5  844.65     183  815.97
   260.1  768.03   317.9  727.95   337.2  716.87   356.4  708.47   385.9     685
   395.7     682   478.9   674.3   484.2  673.65   493.9  674.69   513.7  680.07
   533.4  688.29   602.1  728.21   729.5  793.26   749.1  805.62   768.7  820.58
   798.1  848.12   807.9  854.13   905.8  879.04    1043   906.9  1072.4  910.76
    1141  915.79  1199.8  923.39  1248.7  938.73  1287.9  948.78  1336.9  967.53
#Mann= 3 , 0 , 0
       0      .1       0   478.9    .045       0   493.9      .1       0
Bank Sta=478.9,493.9
XS Rating Curve= 0 ,0
Exp/Cntr=0.3,0.1

Type RM Length L Ch R = 1 ,8829.4  ,997.8,996,992.4
XS GIS Cut Line= 4
     1475134.785      214626.704     1475334.003      215147.971
     1475535.392       215318.11     1476403.448      215439.638
#Sta/Elev= 30
       0   890.9    58.7  892.78   107.7  887.92   215.4  866.36   254.5  856.26
   293.7  841.75   352.4  808.14   460.1  760.42   528.7  744.08   597.1  724.16
   675.2  683.79   704.5  666.42  710.64665.2654   714.3  664.58   728.7  666.56
   743.6  669.58   792.4  672.87   870.4   674.7   889.8  679.82   928.8  705.22
  1006.7  751.39  1094.4  792.21  1123.6   809.7  1152.8  823.79  1201.5  851.42
  1211.2  855.16  1367.1  891.87    1630  926.39  1649.5  930.18  1698.2  945.22
#Mann= 3 , 0 , 0
       0      .1       0  710.64    .045       0   728.7      .1       0
Bank Sta=710.64,728.7
XS Rating Curve= 0 ,0
Exp/Cntr=0.3,0.1

Type RM Length L Ch R = 1 ,7833.4  ,1366,1370,1372.6
XS GIS Cut Line= 4
     1475007.614      215828.527     1475524.976      215908.388
     1475740.253      216047.277     1476184.698      216467.416
#Sta/Elev= 30
       0  902.74    77.6  887.94   164.8  863.23   213.3  852.52   232.7  846.81
     252  838.76   300.5  812.27   339.3  797.37   368.4  783.77   387.8  772.99
   436.2  742.67   465.3  726.76   523.5  697.64   570.9  669.13   580.4  666.53
   608.9  663.32   665.8  660.78   684.8  661.66   732.2  674.12   789.4  701.85
   828.2  717.82   876.8  742.63   925.3  769.19  1012.7  823.85  1032.1  834.93
  1148.6  891.91    1168  895.88  1284.5  908.46  1362.2   922.1  1391.3  921.81
#Mann= 3 , 0 , 0
       0      .1       0   665.8    .045       0   684.8      .1       0
Bank Sta=665.8,684.8
XS Rating Curve= 0 ,0
Exp/Cntr=0.3,0.1

Type RM Length L Ch R = 1 ,6463.4  ,1202.7,1207.4,1210.6
XS GIS Cut Line= 4
     1474743.726      216637.555     1474931.226      216995.194
     1475149.976      217186.166     1475649.976      217477.832
#Sta/Elev= 30
       0  885.58    38.5  876.27   105.8  872.77   173.1  865.61   192.3   861.5
   211.5  854.66   259.6  830.83   307.7  797.23   326.9  781.96   346.1  769.84
   413.5  737.51   452.2  715.86   481.2   695.6   510.3   668.3     520  661.27
   538.8  652.87     549  651.48   553.8  652.23   597.4  660.32   636.1  664.28
   674.8  679.24   723.6   703.6   782.5  737.43   900.2  818.55   919.8  828.26
   968.9  846.19  1116.1  875.23  1155.3  880.46  1214.2  881.02    1273  871.82
#Mann= 3 , 0 , 0
       0      .1       0   538.8    .045       0   553.8      .1       0
Bank Sta=538.8,553.8
XS Rating Curve= 0 ,0
Exp/Cntr=0.3,0.1

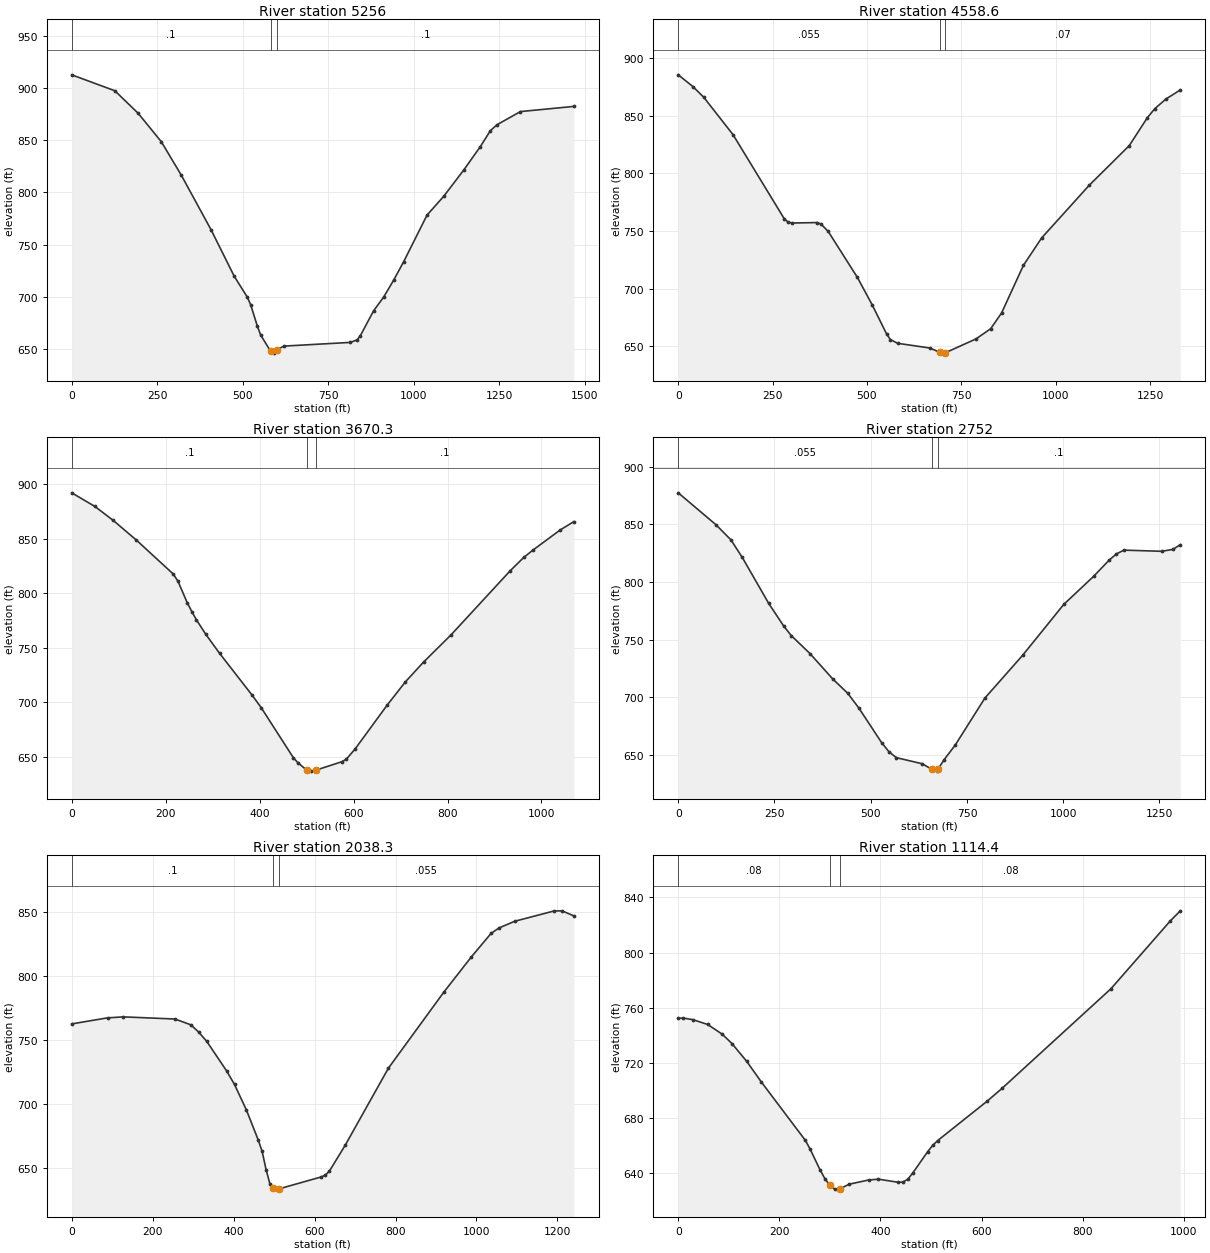
Type RM Length L Ch R = 1 ,5256    ,714.6,697.4,676.5
XS GIS Cut Line= 4
     1473840.948      217147.971     1474215.948      217439.638
     1474382.614      217641.027     1474834.003      218217.416
#Sta/Elev= 30
       0  912.62     126  897.35   193.9  875.88   261.8  848.59     320   816.7
   407.2  764.36   475.1  719.73   513.8  699.48   523.5   692.2   542.8  671.87
   552.5  663.41   581.6   647.8   591.3  646.02   600.5  649.25   620.3  652.74
   814.6  656.29   834.1  658.59   843.9  662.62   882.9  686.58   912.2  699.67
   941.5  715.91   970.8  733.58  1039.1  778.22  1087.9  796.24  1146.5  821.39
  1195.3  843.96  1224.6  859.18  1244.1  864.86  1312.4  877.42  1468.6  882.37
#Mann= 3 , 0 , 0
       0      .1       0   581.6    .045       0   600.5      .1       0
Bank Sta=581.6,600.5
XS Rating Curve= 0 ,0
Exp/Cntr=0.3,0.1

Type RM Length L Ch R = 1 ,4558.6  ,896.3,888.3,877.5
XS GIS Cut Line= 4
     1473445.114      218189.638     1474045.809      218182.694
     1474243.726      218189.638     1474774.976      218206.999
#Sta/Elev= 30
       0  885.51    38.8  875.35    67.8  865.99   145.3  833.58     281  760.66
   290.7  757.82   300.4  757.01   368.2  757.42   377.9  756.21   397.3  749.76
   474.8  709.79   513.5  686.33   552.3  660.68     562  656.01   581.4  652.73
   666.8  648.63   692.8  644.95   704.5  644.21   707.8  644.55   789.3  656.58
   827.8  665.37   856.8  679.05   914.7  720.41   963.1  744.16  1088.7  789.67
    1195  824.13  1243.3  848.51  1262.7  856.15  1291.6  864.41  1330.3   872.4
#Mann= 3 , 0 , 0
       0    .055       0   692.8    .045       0   707.8     .07       0
Bank Sta=692.8,707.8
XS Rating Curve= 0 ,0
Exp/Cntr=0.3,0.1

Type RM Length L Ch R = 1 ,3670.3  ,910,918.3,924.7
XS GIS Cut Line= 4
     1474073.587      219078.527     1474511.087      218901.444
      1474625.67      218859.777     1475087.476      218748.666
#Sta/Elev= 30
       0  892.15    49.2  879.65    88.5  866.76   137.7  848.71   216.3   817.5
   226.2  810.86   245.8   791.3   255.7  783.04   265.5  775.49   285.2  762.36
   314.6  744.86   383.5  706.68   403.2  695.01     472  648.85   481.4  644.42
   500.4  637.52   509.5  636.69   518.9  637.46   575.2  645.36   584.5   647.6
   603.6  657.25   671.4  697.25   710.2   718.6     749  736.83   807.2  761.65
   933.2  820.52   962.3  832.86   981.6  839.51  1039.8  858.05  1068.9  865.73
#Mann= 3 , 0 , 0
       0      .1       0   500.4    .045       0   518.9      .1       0
Bank Sta=500.4,518.9
XS Rating Curve= 0 ,0
Exp/Cntr=0.3,0.1

Type RM Length L Ch R = 1 ,2752    ,706.7,713.7,719.6
XS GIS Cut Line= 4
     1474132.614      219620.194     1474649.976      219727.832
     1474879.142       219724.36     1475424.281      219686.166
#Sta/Elev= 30
       0  877.26    97.9  849.62     137  836.43   166.4  821.21   234.9  781.41
     274  761.72   293.6  753.45   342.5  737.78   401.2   715.9   440.4  703.39
   469.7  690.37   528.4  660.57   547.5  652.67   566.6  647.59   633.5  642.34
   659.6  637.34   671.7  635.92   674.6  637.53   690.8  645.95   719.4  658.47
   796.7  699.36   894.2  736.23  1001.6  780.58  1079.7  805.07  1118.7  818.73
  1138.2  824.31  1157.7  827.57  1255.3  826.56  1284.6  828.17  1304.1  832.28
#Mann= 3 , 0 , 0
       0    .055       0   659.6    .045       0   674.6      .1       0
Bank Sta=659.6,674.6
XS Rating Curve= 0 ,0
Exp/Cntr=0.3,0.1

Type RM Length L Ch R = 1 ,2038.3  ,936.4,923.9,908
XS GIS Cut Line= 4
      1473940.34      219980.871     1474236.781      220206.999
     1474462.476      220269.499     1475087.476      220373.666
#Sta/Elev= 30
       0  762.66    88.3  767.38   127.6  768.16   255.1  766.47   294.4  761.92
     314  756.11   333.6  748.94   382.6  725.88   402.1  715.22   431.4  695.35
   460.7   671.8   470.4  662.85   480.2  648.46   489.9  637.06     497  634.57
   509.4   633.3     512   633.5   616.8  642.88   626.5  644.33   636.3  647.27
   675.3  667.47   782.5  728.05     919  787.38   987.2  815.04  1035.9  833.45
  1055.4  837.73  1094.4     843  1191.9  851.08  1211.4  851.18  1240.6  847.22
#Mann= 3 , 0 , 0
       0      .1       0     497    .045       0     512    .055       0
Bank Sta=497,512
XS Rating Curve= 0 ,0
Exp/Cntr=0.3,0.1

Type RM Length L Ch R = 1 ,1114.4  ,854.6,835,813.4
XS GIS Cut Line= 4
     1474118.726      221147.971     1474360.479      221138.857
     1474521.503      221075.055     1475059.264      220863.249
#Sta/Elev= 30
       0  752.29     9.7  752.48      29  751.33    58.1  747.85    87.1  740.78
   106.4  733.95   135.5  721.07   164.5  706.08   251.6  663.74   261.2  657.22
   280.4  642.51     290  636.09   299.7  631.32   309.3  628.46   320.6  628.83
   338.2  632.04   376.6  635.08   395.9  635.67   434.7  633.46   444.5  633.54
   454.3  635.73   464.1  640.26   493.5  655.69   503.3  660.16   513.1  663.64
     611  692.23   640.4  701.49     856  773.78   973.5  823.01   993.1  830.23
#Mann= 3 , 0 , 0
       0     .08       0   299.7    .045       0   320.6     .08       0
Bank Sta=299.7,320.6
XS Rating Curve= 0 ,0
Exp/Cntr=0.3,0.1

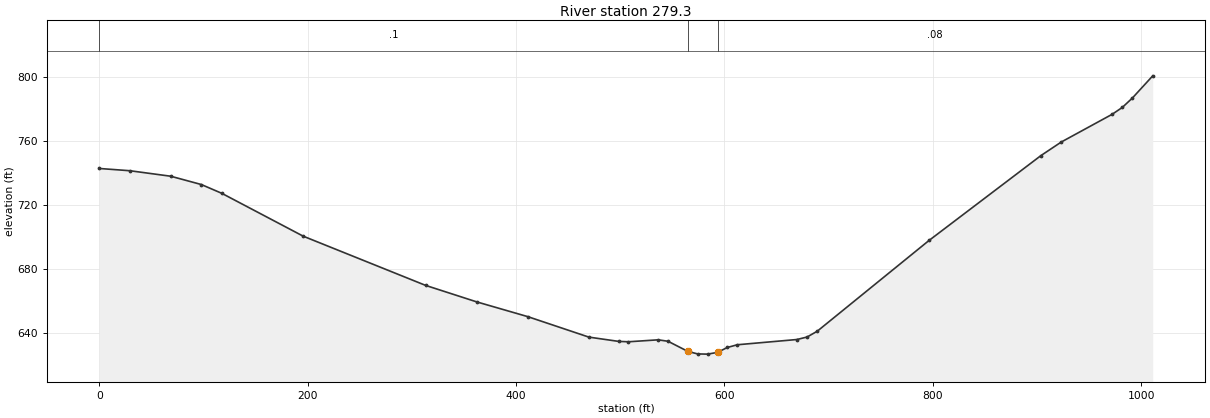
Type RM Length L Ch R = 1 ,279.3   ,282.7,279.3,272.5
XS GIS Cut Line= 4
     1474639.559      221797.277     1475045.809      221561.166
     1475104.837       221380.61     1475177.753       221036.86
#Sta/Elev= 30
       0  743.07    29.4  741.66    68.5  738.23    97.9  733.04   117.5  727.56
   195.8  700.72   313.2  669.99   362.2  659.69   411.2  650.47   469.9  637.66
   498.4  634.99   507.9  634.74   536.4  635.96   545.9  635.06   564.9  628.74
   574.4  627.14   583.9  627.02   593.4  628.11   602.8  631.17   612.4  632.88
   669.6  636.15   679.4  637.72   689.1  641.32   796.5   698.1   903.9  751.15
   923.4  759.61   972.2  776.93     982  781.24   991.7  787.14  1011.2  800.99
#Mann= 3 , 0 , 0
       0      .1       0   564.9    .045       0   593.4     .08       0
Bank Sta=564.9,593.4
XS Rating Curve= 0 ,0
Exp/Cntr=0.3,0.1

Chan Stop Cuts=-1
Use User Specified Reach Order=0
Composite Channel Slope=5